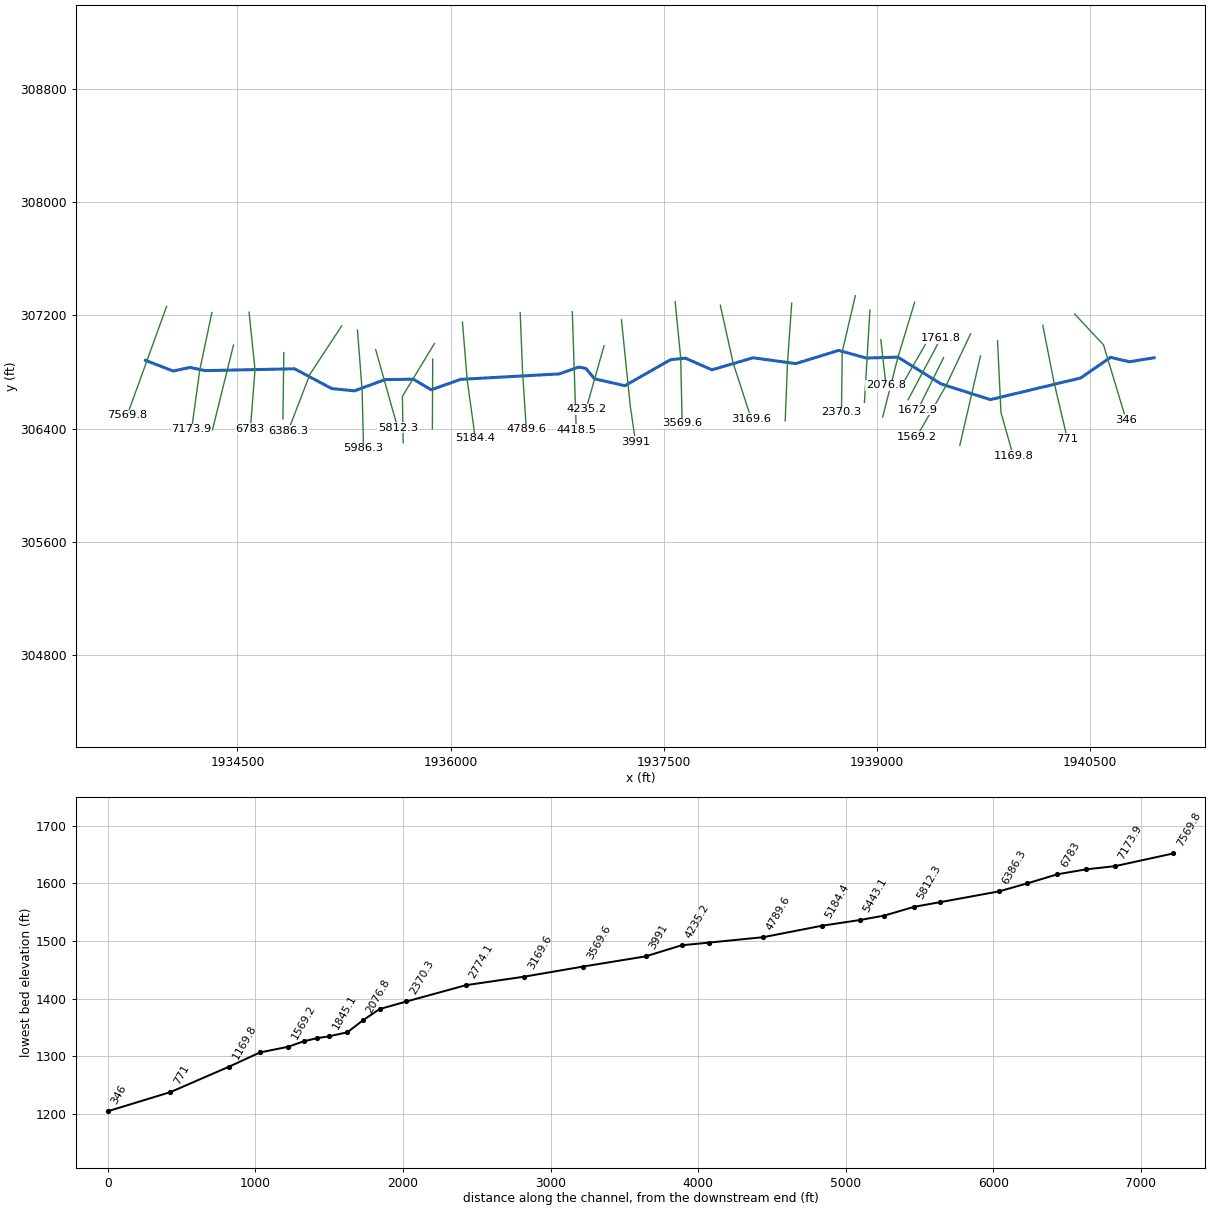
--- BtffCrk.prj (project) ---

Proj Title=BtffCrk
Current Plan=p01
Default Exp/Contr=0,0
English Units
Geom File=g01
Flow File=f01
Plan File=p01
BEGIN DESCRIPTION:
END DESCRIPTION:
DSS Export Rating Curves= 0
DSS Export Rating Curve Sorted= 0
DSS Export Volume Flow Curves= 0
DXF OffsetX= 0
DXF OffsetY= 0
DXF ScaleX= 0
DXF ScaleY= 0

--- BtffCrk.p01 (plan) ---

Plan Title=Floodplain
Program Version=4.00
Geom File=g01
Flow File=f01
K Sum by GR=0
Std Step Tol=0.01
Critical Tol=0.01
Num of Std Step Trials=20
Max Error Tol=0.3
Flow Tol Ratio=0.001
Split Flow NTrial=30
Split Flow Tol=0.02
Split Flow Ratio=0.02
Log Output Level=0
Friction Slope Method=1
Unsteady Friction Slope Method=2
Unsteady Bridges Friction Slope Method=1
Global Log Level=0
CheckData=False
Run HTab=0
Run UNet=0
Run PostProcess=0
UNET Theta=0
UNET Theta Warmup=0
UNET ZTol=0
UNET ZSATol=0
UNET MxIter=0
UNET MaxInSteps=0
UNET DtIC=0
UNET DtMin=0
UNET MaxCRTS=0
UNET WFStab=0
UNET SFStab=0
UNET WFX=0
UNET SFX=0
UNET DSS MLevel=0
UNET DZMax Abort=0
UNET Convert EG Bridges=0
UNET Use Existing IB Tables=0
UNET Froude Limit=0
UNET Froude Power=0
Write IC File=0
Echo Input=False
Echo Output=False
Write Detailed=0

--- BtffCrk.f01 (steady flow) ---

Flow Title=NFF Regression Equation
Program Version=4.00
Number of Profiles=1
Profile Names=P100yr
River Rch & RM=BtffCrk,Main      ,7569.8
594.3168
River Rch & RM=BtffCrk,Main      ,5986.3
624.0981
River Rch & RM=BtffCrk,Main      ,5609.7
728.5631
River Rch & RM=BtffCrk,Main      ,4418.5
747.4874
Boundary for River Rch & Prof#=BtffCrk,Main      ,1
Up Type=0
Dn Type=3
Dn Slope=0.102147

--- BtffCrk.g01 (geometry) ---

Geom Title=USGS 3m DEM
Program Version=4.10

River Reach=BtffCrk         ,Main
Reach XY= 30
     1933852.826      306881.489     1934047.599      306806.584
     1934165.072       306831.77     1934272.344      306809.383
     1934901.984      306822.442     1935163.154      306682.951
     1935323.128      306666.537     1935538.154      306745.952
     1935737.928      306748.906      1935864.42      306674.386
     1936071.716      306747.818     1936765.002      306786.137
     1936902.841      306834.568     1936954.145      306824.307
     1937013.844      306751.549     1937227.838      306703.067
     1937549.125      306886.424      1937654.63      306896.844
     1937840.109      306815.062     1938130.406      306899.864
     1938430.937      306859.064     1938732.995      306952.101
     1938927.201      306898.135     1939149.934      306904.646
     1939453.293      306715.793     1939800.888      306604.802
     1940436.832       306757.45     1940647.842      306903.331
     1940779.415      306871.874     1940953.692      306900.087

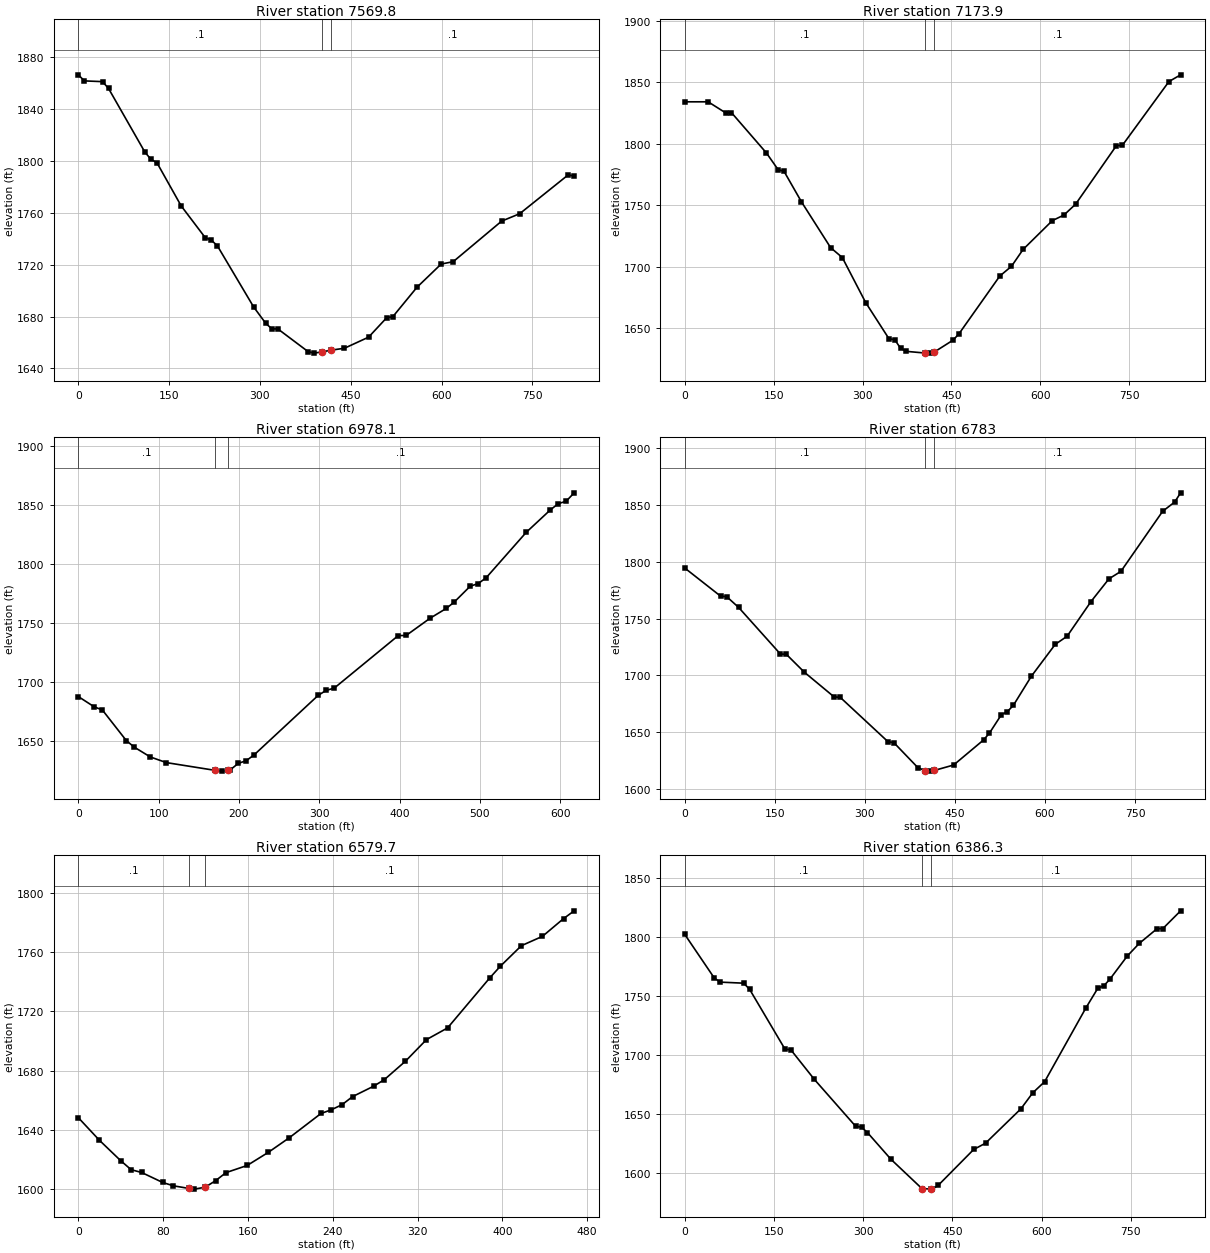
Type RM Length L Ch R = 1 ,7569.8  ,389.3,395.7,398.3
XS GIS Cut Line= 3
     1934001.313      307263.251     1933862.232      306878.093
     1933723.151      306492.935
#Sta/Elev= 30
       0 1866.15      10 1861.48      40  1860.9    49.9 1855.64   109.9 1806.66
   119.8 1801.13   129.8 1798.48   169.8 1765.24   209.7 1740.68   219.7 1738.84
   229.7 1734.42   289.6 1687.34   309.6 1674.71   319.6 1670.54   329.6 1670.43
   379.5 1652.96   389.5 1651.79     402 1652.69     417 1654.04   439.5 1655.54
   479.4 1664.08   509.4 1679.09   519.4 1679.81   559.3 1702.48   599.3  1720.4
   619.2 1722.22   699.2 1753.46   729.1 1759.19     809 1789.03     819 1788.22
#Mann= 3 , 0 , 0
       0      .1       0     402    .045       0     417      .1       0
Bank Sta=402,417
XS Rating Curve= 0 ,0
Exp/Cntr=0.3,0.1

Type RM Length L Ch R = 1 ,7173.9  ,199.7,195.8,193.3
XS GIS Cut Line= 3
     1934319.823      307219.494     1934234.845      306814.873
     1934176.882      306395.589
#Sta/Elev= 30
       0 1833.95    39.4 1833.96    68.9 1824.99    78.8 1825.14   137.8 1792.36
   157.5 1778.81   167.4  1777.5   196.9 1752.64   246.1 1715.43   265.8 1707.39
   305.2 1670.84   344.5 1641.42   354.4 1640.59   364.2 1633.56   374.1 1631.14
   405.9 1629.76   413.4 1629.71   420.9 1630.57   452.8  1640.3   462.7 1645.44
   531.6 1692.38   551.3 1700.29   570.9 1714.01   620.2 1737.39   639.8 1741.94
   659.5 1750.77   728.4 1798.39   738.3 1798.51     817 1850.44   836.7 1855.89
#Mann= 3 , 0 , 0
       0      .1       0   405.9    .045       0   420.9      .1       0
Bank Sta=405.9,420.9
XS Rating Curve= 0 ,0
Exp/Cntr=0.3,0.1

Type RM Length L Ch R = 1 ,6978.1  ,187.2,195,198.7
XS GIS Cut Line= 2
     1934471.807      306989.879     1934323.803        306390.4
#Sta/Elev= 30
       0 1687.44    19.9 1678.68    29.9 1676.09    59.8 1650.07    69.7 1644.51
    89.6 1636.22   109.6 1631.42   170.8 1624.79   179.3 1624.19   185.8 1624.93
   189.2 1625.31   199.2 1630.73   209.2 1633.09   219.1 1638.07   298.8 1688.51
   308.7  1692.7   318.7 1694.59   398.4 1739.14   408.3 1739.28   438.2 1753.94
   458.1 1762.14   468.1 1767.55     488 1781.02     498 1783.28   507.9  1788.2
   557.7 1826.66   587.6 1845.61   597.6 1851.02   607.5 1853.11   617.5 1860.25
#Mann= 3 , 0 , 0
       0      .1       0   170.8    .045       0   185.8      .1       0
Bank Sta=170.8,185.8
XS Rating Curve= 0 ,0
Exp/Cntr=0.3,0.1

Type RM Length L Ch R = 1 ,6783    ,205.8,203,204.5
XS GIS Cut Line= 3
     1934581.491      307221.489     1934623.652      306815.644
     1934590.833      306399.102
#Sta/Elev= 30
       0 1794.41    59.7 1769.65    69.7 1769.28    89.6 1759.79   159.2 1718.74
   169.2 1718.44     199 1702.78   248.8 1680.92   258.8 1680.64   338.4 1641.56
   348.3 1640.66   388.1 1618.77   400.5 1616.02     408 1615.62   415.5  1616.2
   447.8 1621.01   497.6 1643.05   507.5 1649.15   527.4 1665.34   537.4 1668.07
   547.3 1673.53   577.2 1699.11     617 1727.21   636.8 1734.38   676.6 1764.92
   706.5 1784.92   726.4 1791.49     796 1844.41   815.9 1852.49   825.9 1860.65
#Mann= 3 , 0 , 0
       0      .1       0   400.5    .045       0   415.5      .1       0
Bank Sta=400.5,415.5
XS Rating Curve= 0 ,0
Exp/Cntr=0.3,0.1

Type RM Length L Ch R = 1 ,6579.7  ,206.2,193.5,185.5
XS GIS Cut Line= 2
     1934826.272      306936.399     1934820.053      306468.755
#Sta/Elev= 30
       0 1648.17    19.9  1632.9    39.8 1619.24    49.8 1613.05    59.7 1611.16
    79.6 1604.41    89.6 1602.17   104.6 1600.35   109.5 1599.92   119.6 1601.22
   129.4 1605.58   139.3 1611.07   159.2 1615.88   179.1  1624.7     199 1634.62
   228.9 1651.01   238.8 1653.54   248.8 1656.97   258.7  1662.4   278.6 1669.44
   288.6 1673.82   308.5 1686.26   328.4 1700.89   348.3 1708.78   388.1 1742.56
     398 1750.38   417.9  1764.3   437.8 1770.62   457.7 1782.59   467.7 1787.85
#Mann= 3 , 0 , 0
       0      .1       0   104.6    .045       0   119.6      .1       0
Bank Sta=104.6,119.6
XS Rating Curve= 0 ,0
Exp/Cntr=0.3,0.1

Type RM Length L Ch R = 1 ,6386.3  ,385,399.7,408.4
XS GIS Cut Line= 3
     1935233.263      307124.339     1935010.695      306784.448
     1934857.274      306385.149
#Sta/Elev= 30
       0 1802.23    49.6 1765.26    59.5 1761.76    99.1 1760.86     109 1755.65
   168.5 1704.83   178.4 1704.26     218 1679.09   287.4 1639.28   297.3 1638.54
   307.2 1633.98   346.8 1611.25   398.8 1586.43   413.8 1585.98   416.2 1585.93
   426.2 1589.12   485.9  1619.6   505.8 1624.94   565.4 1654.18   585.3 1667.74
   605.2 1677.15   674.9 1740.07   694.8 1756.62   704.7 1758.61   714.7 1764.03
   744.5 1784.07   764.4 1794.63   794.2 1807.08   804.2 1807.29     834 1822.32
#Mann= 3 , 0 , 0
       0      .1       0   398.8    .045       0   413.8      .1       0
Bank Sta=398.8,413.8
XS Rating Curve= 0 ,0
Exp/Cntr=0.3,0.1

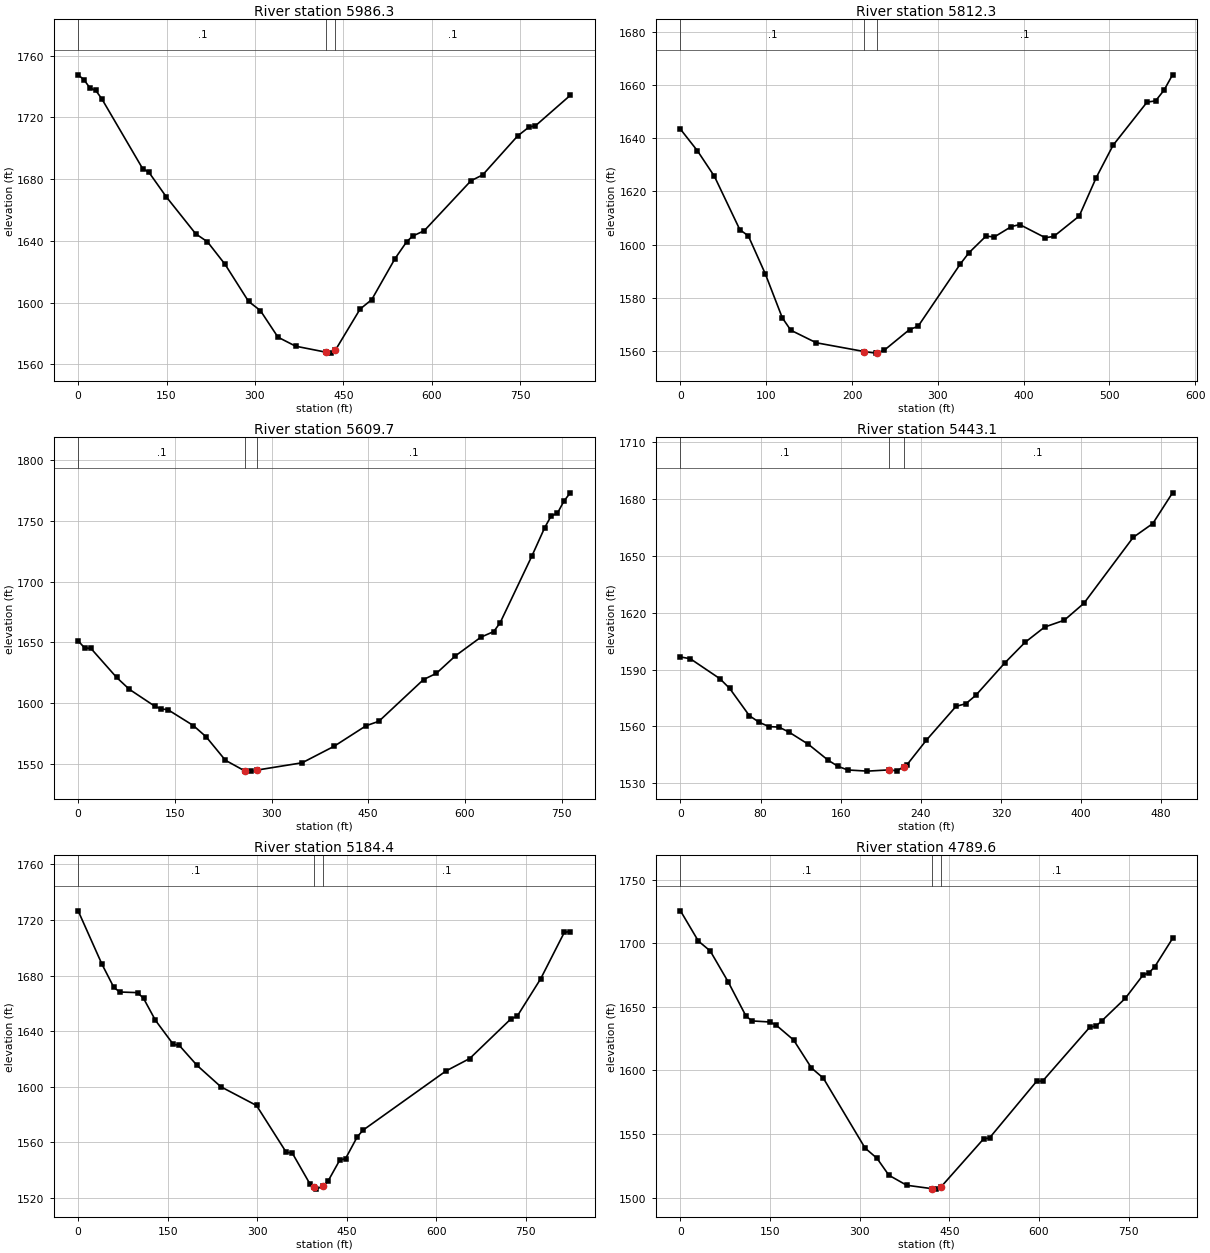
Type RM Length L Ch R = 1 ,5986.3  ,169.5,174,179.7
XS GIS Cut Line= 3
     1935344.879      307095.464     1935377.737      306667.853
     1935387.523      306261.889
#Sta/Elev= 30
       0  1747.5      10 1744.24      20    1739    29.9 1737.36    39.9 1732.11
   109.7 1686.57   119.7 1684.57   149.6 1668.45   199.5 1644.52   219.4 1639.36
   249.3 1624.75   289.2 1600.72   309.2 1594.83   339.1 1577.57     369 1571.74
   421.4 1567.78   428.9 1567.24   436.4  1569.1   478.4 1595.75   498.2 1601.91
   537.8 1628.52   557.6 1639.44   567.5 1643.03   587.3 1646.53   666.6  1678.9
   686.4 1682.65   745.8 1707.92   765.6 1713.82   775.5 1714.32     835 1734.19
#Mann= 3 , 0 , 0
       0      .1       0   421.4    .045       0   436.4      .1       0
Bank Sta=421.4,436.4
XS Rating Curve= 0 ,0
Exp/Cntr=0.3,0.1

Type RM Length L Ch R = 1 ,5812.3  ,221.3,202.3,182.8
XS GIS Cut Line= 2
     1935473.013      306957.542      1935628.48      306405.325
#Sta/Elev= 30
       0 1643.38    19.8 1635.26    39.6 1625.66    69.2 1605.64    79.1 1603.31
    98.9 1589.05   118.7 1572.54   128.6 1567.88   158.3 1563.16   214.3 1559.86
   227.5 1559.27   229.3 1559.46   237.4 1560.31   267.1 1568.14     277 1569.33
   326.4 1592.82   336.3 1596.96   356.1  1603.2     366 1602.93   385.8 1606.82
   395.6 1607.55   425.3 1602.63   435.2  1603.1   464.9 1610.77   484.7 1625.19
   504.4 1637.37     544 1653.56   553.9 1654.02   563.8 1658.06   573.7 1663.81
#Mann= 3 , 0 , 0
       0      .1       0   214.3    .045       0   229.3      .1       0
Bank Sta=214.3,229.3
XS Rating Curve= 0 ,0
Exp/Cntr=0.3,0.1

Type RM Length L Ch R = 1 ,5609.7  ,153.4,166.3,179.9
XS GIS Cut Line= 3
     1935887.176      307001.384     1935661.283      306627.486
     1935666.664      306301.057
#Sta/Elev= 30
       0 1651.25     9.9 1645.41    19.9 1644.94    59.6 1621.15    79.4 1611.36
   119.1 1597.37   129.1 1595.16     139 1594.66   178.7 1581.54   198.6 1572.26
   228.4 1553.01   258.1 1544.36   268.1 1544.07     278 1544.98   347.5 1550.94
   397.1 1564.52   446.7 1581.41   466.5 1585.06   535.8 1619.39   555.6 1624.44
   585.2 1638.85   624.8 1654.24   644.6 1658.81   654.5 1665.97     704 1721.13
   723.7 1744.25   733.6  1753.8   743.5 1756.19   753.4 1765.92   763.3 1772.92
#Mann= 3 , 0 , 0
       0      .1       0   258.1    .045       0     278      .1       0
Bank Sta=258.1,278
XS Rating Curve= 0 ,0
Exp/Cntr=0.3,0.1

Type RM Length L Ch R = 1 ,5443.1  ,256.5,258.4,261.1
XS GIS Cut Line= 2
     1935874.739      306890.692     1935872.252      306399.417
#Sta/Elev= 30
       0 1596.65     9.8 1595.71    39.3 1585.19    49.1 1580.04    68.8 1565.62
    78.6 1562.13    88.4 1559.86    98.3 1559.61   108.1 1557.04   127.7 1550.52
   147.4 1542.13   157.2 1538.89     167 1536.96   186.7 1536.35   207.7 1536.99
   216.2 1536.52   222.7 1538.57     226 1539.61   245.6 1552.76   275.1 1570.56
   284.9 1571.95   294.8 1576.37   324.2 1593.71   343.9  1604.3   363.6 1612.44
   383.2 1616.04   402.8 1624.99     452  1659.8   471.6 1667.12   491.3 1683.33
#Mann= 3 , 0 , 0
       0      .1       0   207.7    .045       0   222.7      .1       0
Bank Sta=207.7,222.7
XS Rating Curve= 0 ,0
Exp/Cntr=0.3,0.1

Type RM Length L Ch R = 1 ,5184.4  ,395,394.6,393.3
XS GIS Cut Line= 3
     1936084.118      307151.324     1936117.379       306744.32
     1936174.463      306332.301
#Sta/Elev= 30
       0 1726.66    39.8 1688.33    59.8 1671.55    69.7 1668.25    99.6  1667.8
   109.6 1663.63   129.5 1647.87   159.4 1630.57   169.3 1629.87   199.2 1615.44
     239 1600.08   298.8 1586.59   348.6  1552.9   358.6 1552.46   388.4 1530.08
     395 1527.66   398.4 1526.41     410 1528.51   418.3 1531.93   438.1 1547.18
     448 1548.41   467.8 1564.22   477.7 1568.98   616.3 1611.45     656  1620.4
   725.3 1649.05   735.2 1650.63   774.8 1677.74   814.4 1711.14   824.3 1711.78
#Mann= 3 , 0 , 0
       0      .1       0     395    .045       0     410      .1       0
Bank Sta=395,410
XS Rating Curve= 0 ,0
Exp/Cntr=0.3,0.1

Type RM Length L Ch R = 1 ,4789.6  ,371.9,370.7,369.5
XS GIS Cut Line= 3
     1936490.616      307218.678     1936506.898      306810.471
     1936533.413      306396.332
#Sta/Elev= 30
       0 1725.39    29.9 1701.65    49.8 1693.85    79.7 1669.68   109.6  1642.7
   119.6 1638.87   149.5 1638.03   159.4 1635.86   189.3  1623.9   219.2 1601.91
   239.1 1593.88   308.9 1538.98   328.8 1530.94   348.8 1517.59   378.6 1509.72
   421.6    1507   428.3 1506.68   436.6 1508.73   507.3 1546.17   517.2 1546.92
   596.3 1591.58   606.1 1591.59   685.2 1634.05   695.1 1634.66     705 1638.86
   744.5 1656.68   774.1 1674.92     784 1676.58   793.9 1681.58   823.5 1703.67
#Mann= 3 , 0 , 0
       0      .1       0   421.6    .045       0   436.6      .1       0
Bank Sta=421.6,436.6
XS Rating Curve= 0 ,0
Exp/Cntr=0.3,0.1

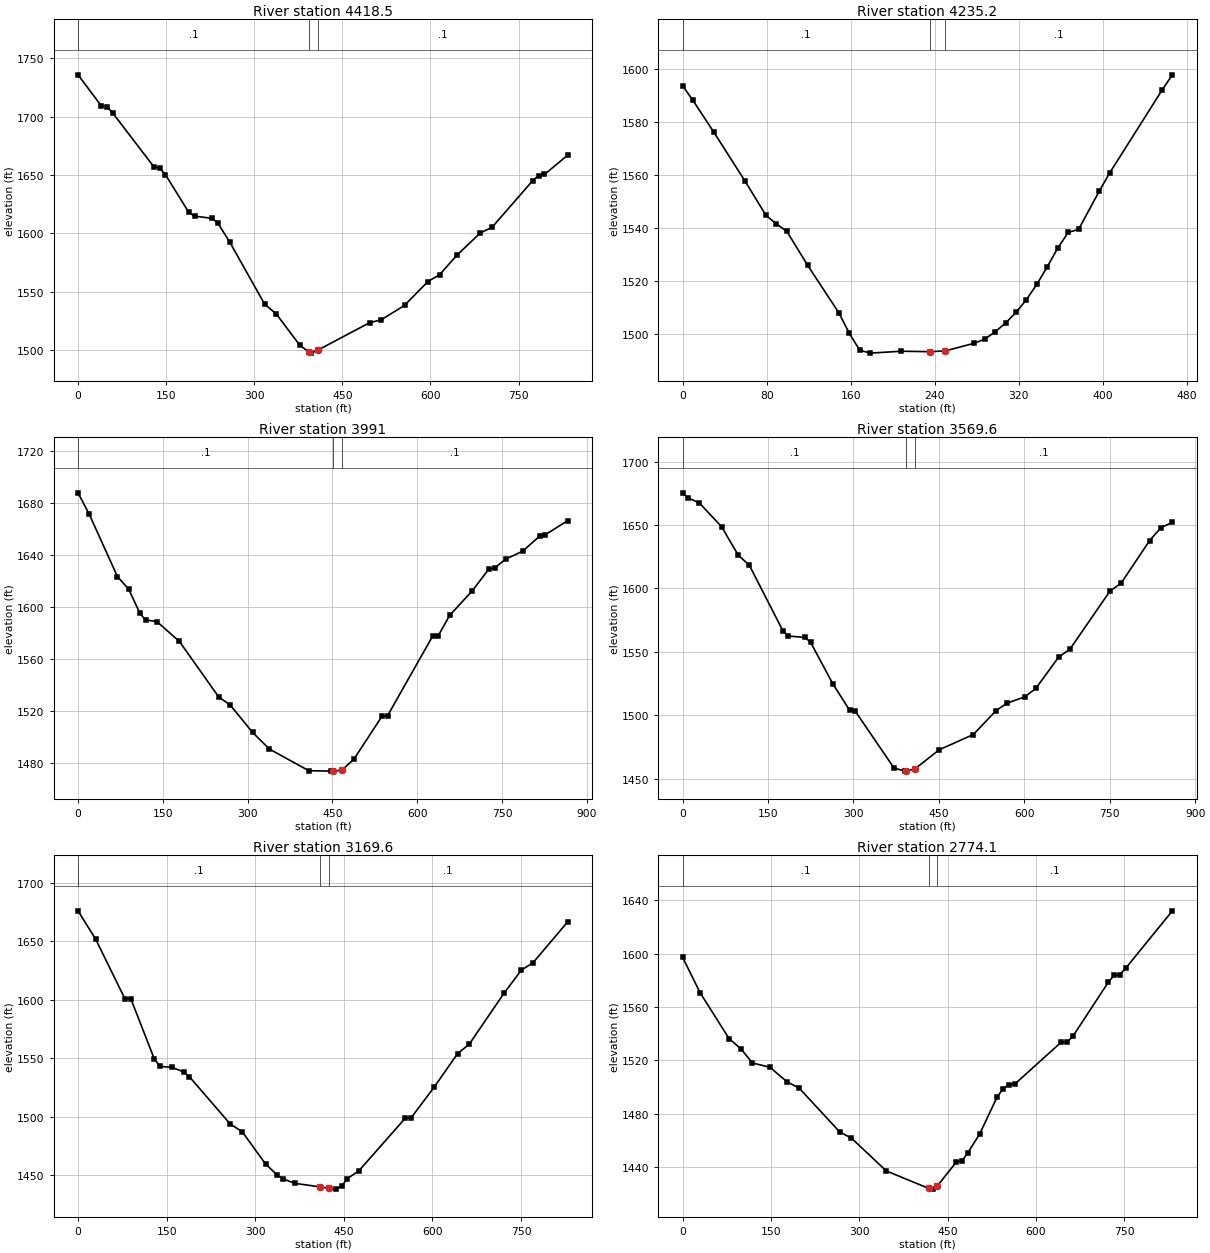
Type RM Length L Ch R = 1 ,4418.5  ,189.2,183.5,177.1
XS GIS Cut Line= 2
     1936857.387      307224.761      1936885.38      306391.461
#Sta/Elev= 30
       0 1735.94    39.7 1709.28    49.6 1708.45    59.6 1702.85     129 1657.07
     139 1655.78   148.9 1650.25   188.6 1617.93   198.5  1614.7   228.3 1612.82
   238.2 1608.62   258.1 1592.62   317.6 1539.24   337.5 1530.82   377.2 1504.18
   393.8 1497.79     397  1497.2   408.8 1499.91   496.3 1523.29   516.1  1525.8
   555.8 1538.12   595.6  1558.6   615.4 1564.43   645.2 1581.29   684.9 1600.34
   704.7 1605.06   774.2 1645.26   784.1  1649.5   794.1 1650.49   833.8 1667.14
#Mann= 3 , 0 , 0
       0      .1       0   393.8    .045       0   408.8      .1       0
Bank Sta=393.8,408.8
XS Rating Curve= 0 ,0
Exp/Cntr=0.3,0.1

Type RM Length L Ch R = 1 ,4235.2  ,235.5,243.8,252.6
XS GIS Cut Line= 2
     1937081.006      306984.749     1936954.145      306536.072
#Sta/Elev= 30
       0 1593.61     9.9 1588.05    29.8 1576.02    59.5 1557.57    79.4 1544.62
    89.3 1541.42    99.2 1538.63     119 1525.81   148.8 1507.82   158.7  1500.1
   168.6 1493.73   178.6 1492.62   208.3 1493.34   235.2 1493.17   250.2 1493.47
   277.8 1496.36   287.7 1497.92   297.6 1500.68   307.5    1504   317.5 1508.01
   327.4 1512.86   337.3 1518.64   347.2 1525.23   357.1 1532.26   367.1  1538.2
     377 1539.36   396.8  1553.9   406.7 1560.73   456.4 1591.92   466.3 1597.73
#Mann= 3 , 0 , 0
       0      .1       0   235.2    .045       0   250.2      .1       0
Bank Sta=235.2,250.2
XS Rating Curve= 0 ,0
Exp/Cntr=0.3,0.1

Type RM Length L Ch R = 1 ,3991    ,421.4,421.4,419.6
XS GIS Cut Line= 3
     1937203.599      307167.623     1937265.234      306563.279
     1937302.546       306307.07
#Sta/Elev= 30
       0 1687.67    19.9 1671.12    69.7 1623.23    89.6 1613.47   109.6  1594.8
   119.5 1589.79   139.4 1588.56   179.3 1573.29     249 1530.43   268.9 1524.46
   308.7 1503.26   338.6 1490.39   408.3 1473.74   448.1 1473.42   451.8 1473.42
   466.8 1474.22     488 1482.61   537.8 1515.74   547.7 1516.21   627.4 1577.42
   637.4 1577.78   657.3 1593.27   697.1  1612.1     727 1629.08   736.9 1629.86
   756.8  1636.7   786.7 1642.76   816.6 1654.38   826.6 1655.46   866.4 1666.27
#Mann= 3 , 0 , 0
       0      .1       0   451.8    .045       0   466.8      .1       0
Bank Sta=451.8,466.8
XS Rating Curve= 0 ,0
Exp/Cntr=0.3,0.1

Type RM Length L Ch R = 1 ,3569.6  ,397.2,400,406.7
XS GIS Cut Line= 3
     1937581.621      307296.246     1937620.888      306897.559
     1937630.966      306438.291
#Sta/Elev= 30
       0 1675.45     9.8 1671.41    29.3  1667.5    68.4 1648.76    97.7 1626.26
   117.2 1618.29   175.9 1566.75   185.6 1562.48     215 1561.31   224.7 1557.52
   263.8 1524.75   293.1 1503.99   302.9 1503.34   371.3 1458.24   390.8 1455.86
   393.1 1456.01   408.1  1457.7   450.6 1472.71   510.5 1484.73   550.4 1503.65
   570.4 1509.65   600.4 1514.36   620.3 1521.12   660.3 1545.85   680.2 1552.13
   750.1 1597.73   770.1 1604.24     820 1637.73     840 1648.01     860 1652.11
#Mann= 3 , 0 , 0
       0      .1       0   393.1    .045       0   408.1      .1       0
Bank Sta=393.1,408.1
XS Rating Curve= 0 ,0
Exp/Cntr=0.3,0.1

Type RM Length L Ch R = 1 ,3169.6  ,401.6,395.2,387.3
XS GIS Cut Line= 3
     1937899.771        307270.6     1937989.772       306863.73
     1938116.867      306471.338
#Sta/Elev= 30
       0 1675.86    29.8  1651.7    79.4 1600.76    89.3 1600.96     129 1549.59
   138.9 1543.07   158.8 1542.26   178.6 1538.45   188.5 1534.26     258 1493.73
   277.8  1487.4   317.5 1459.79   337.3 1450.27   347.2 1447.02   367.1 1443.25
   409.2 1440.27   424.2 1439.14   436.4 1438.31   446.2 1440.81     456 1447.32
   475.6 1454.02   554.2 1498.96     564 1499.25   603.3 1525.59   642.6 1554.04
   662.2 1561.92   721.1 1605.45   750.6 1625.27   770.2 1631.51   829.2 1666.58
#Mann= 3 , 0 , 0
       0      .1       0   409.2    .045       0   424.2      .1       0
Bank Sta=409.2,424.2
XS Rating Curve= 0 ,0
Exp/Cntr=0.3,0.1

Type RM Length L Ch R = 1 ,2774.1  ,407.4,403.7,403.5
XS GIS Cut Line= 3
     1938402.232        307285.6     1938372.638      306861.351
     1938356.697      306454.948
#Sta/Elev= 30
       0 1597.15    29.7 1570.66    79.1  1536.2    98.9  1528.7   118.7 1518.02
   148.4 1514.78     178 1503.74   197.8 1499.33     267 1466.32   286.8 1461.75
   346.2 1437.14   417.8 1424.16   425.3 1423.56   432.8 1426.06     465 1443.82
   474.9 1444.95   484.8 1450.96   504.6 1464.86   534.4 1492.61   544.3 1498.69
   554.2 1501.86   564.2 1502.18   643.5 1533.73   653.4 1533.75   663.4 1538.27
   722.9 1578.35   732.8 1583.63   742.7 1584.18   752.6 1588.95     832 1631.96
#Mann= 3 , 0 , 0
       0      .1       0   417.8    .045       0   432.8      .1       0
Bank Sta=417.8,432.8
XS Rating Curve= 0 ,0
Exp/Cntr=0.3,0.1

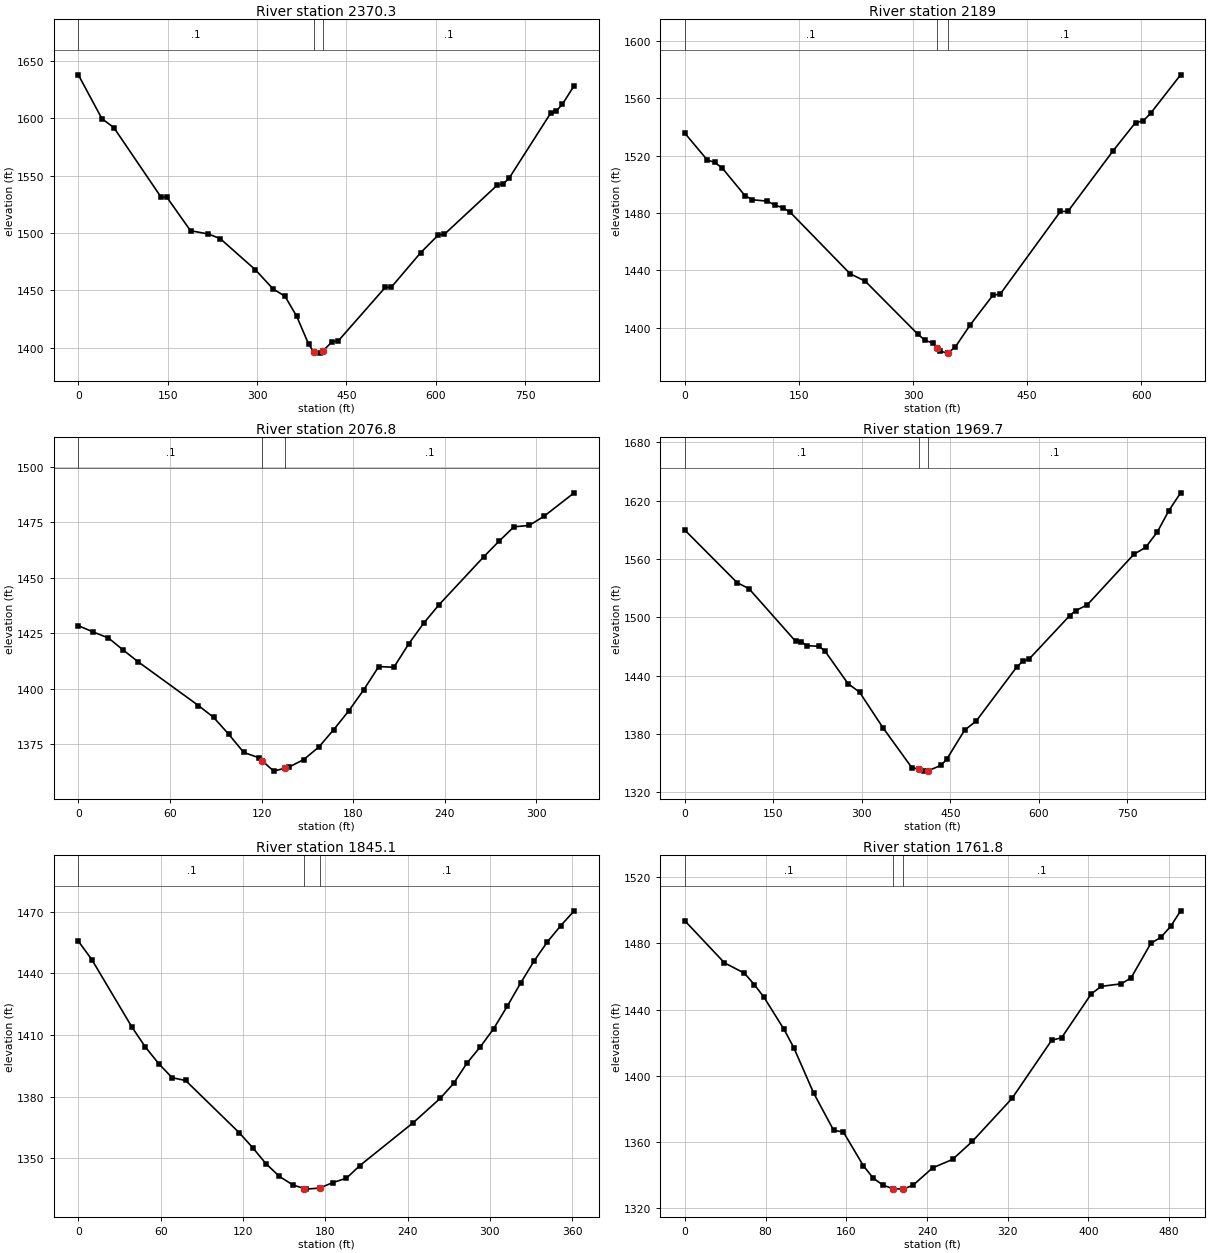
Type RM Length L Ch R = 1 ,2370.3  ,177.4,181.2,180.9
XS GIS Cut Line= 3
     1938850.302      307338.108     1938758.031       306942.38
     1938752.753      306516.458
#Sta/Elev= 30
       0 1638.05    39.6 1599.77    59.5 1592.09   138.8 1531.39   148.7 1531.16
   188.3 1502.07     218  1499.2   237.9 1495.26   297.3 1467.92   327.1 1451.18
   346.9  1444.9   366.7 1427.25   386.5 1403.16     395  1396.5   406.3 1395.26
     410 1396.91   426.2 1405.28   436.1 1405.79   515.3 1452.67   525.2 1452.68
   574.7 1482.92   604.5 1498.46   614.4 1498.92   703.5 1541.96   713.4 1542.94
   723.3 1548.01   792.7  1604.5   802.6 1606.71   812.5 1612.32   832.3 1628.63
#Mann= 3 , 0 , 0
       0      .1       0     395    .045       0     410      .1       0
Bank Sta=395,410
XS Rating Curve= 0 ,0
Exp/Cntr=0.3,0.1

Type RM Length L Ch R = 1 ,2189    ,108.3,112.2,116.1
XS GIS Cut Line= 2
      1938952.98      307236.139     1938914.425      306585.666
#Sta/Elev= 30
       0 1535.78    29.6 1516.99    39.5 1515.36    49.4  1511.3      79  1492.2
    88.9 1489.25   108.6 1488.31   118.5 1485.51   128.4 1483.78   138.2 1480.72
   217.2 1437.62     237 1432.47   306.1  1395.5   315.9 1391.04   325.8 1389.28
   331.5 1385.97   335.7 1383.53   345.6 1382.18   346.5 1382.57   355.4 1386.42
   375.2 1401.99   404.8 1422.54   414.7 1423.53   493.6  1481.1   503.5 1481.16
   562.8 1523.42   592.4 1543.21   602.2 1544.24   612.1  1549.6   651.6 1576.51
#Mann= 3 , 0 , 0
       0      .1       0   331.5    .045       0   346.5      .1       0
Bank Sta=331.5,346.5
XS Rating Curve= 0 ,0
Exp/Cntr=0.3,0.1

Type RM Length L Ch R = 1 ,2076.8  ,116.3,107.1,98.9
XS GIS Cut Line= 2
     1939029.626      307028.591     1939066.005      306705.842
#Sta/Elev= 30
       0 1428.49     9.8 1425.62    19.7 1422.95    29.5 1417.43    39.4 1412.09
    78.7 1392.47    88.6 1387.16    98.4 1379.64   108.3 1371.38   118.1 1368.99
   120.6 1367.46     128 1362.92   135.6 1364.29   137.8 1364.69   147.6 1368.11
   157.5 1373.75   167.3 1381.63   177.2 1390.13     187 1399.62   196.8 1410.07
   206.7 1409.72   216.5 1420.37   226.4 1429.73   236.2 1437.86   265.7 1459.63
   275.6 1466.59   285.4 1473.07   295.3 1473.65   305.1 1477.83   324.8 1488.37
#Mann= 3 , 0 , 0
       0      .1       0   120.6    .045       0   135.6      .1       0
Bank Sta=120.6,135.6
XS Rating Curve= 0 ,0
Exp/Cntr=0.3,0.1

Type RM Length L Ch R = 1 ,1969.7  ,129.8,124.5,118.3
XS GIS Cut Line= 3
     1939267.983      307291.702     1939150.503      306904.421
     1939042.907      306482.497
#Sta/Elev= 30
       0 1589.71    88.8 1535.55   108.6 1529.54   187.6 1475.45   197.4  1474.6
   207.3 1470.87     227 1470.17   236.9 1465.82   276.4 1431.91   296.1 1423.03
   335.6 1386.62     385 1345.15   397.2 1344.22   404.7 1341.86   412.2 1342.29
   434.4 1347.84   444.3 1354.56     474 1383.92   493.8 1393.44     563 1449.37
   572.9 1454.86   582.8 1456.71   652.1 1501.67     662  1506.8   681.8 1512.74
     761 1564.87   780.8 1571.86   800.6 1587.77   820.3 1609.81   840.1 1627.98
#Mann= 3 , 0 , 0
       0      .1       0   397.2    .045       0   412.2      .1       0
Bank Sta=397.2,412.2
XS Rating Curve= 0 ,0
Exp/Cntr=0.3,0.1

Type RM Length L Ch R = 1 ,1845.1  ,82.2,83.1,84
XS GIS Cut Line= 2
     1939342.114      306992.211     1939162.083      306678.791
#Sta/Elev= 30
       0 1455.59     9.8 1446.66    39.1 1413.75    48.8 1404.15    58.6 1395.97
    68.4 1389.15    78.2  1387.8   117.2 1362.43     127 1355.18   136.8 1347.29
   146.5 1341.16   156.3 1336.99   164.7 1335.23   166.1 1334.94   175.8 1335.46
   185.6 1338.15   195.4 1340.25   205.2 1346.41   244.2 1367.33   263.8 1379.13
   273.5 1386.35   283.3  1396.3   293.1 1404.25   302.8 1413.09   312.6  1423.9
   322.4 1435.23   332.1 1445.85   341.9 1455.27   351.7  1463.2   361.4 1470.36
#Mann= 3 , 0 , 0
       0      .1       0   164.7    .045       0   175.8      .1       0
Bank Sta=164.7,175.8
XS Rating Curve= 0 ,0
Exp/Cntr=0.3,0.1

Type RM Length L Ch R = 1 ,1761.8  ,88.6,89.1,89.6
XS GIS Cut Line= 2
     1939221.627        306603.7     1939451.718      307037.763
#Sta/Elev= 30
       0 1493.71    39.3 1468.28      59 1462.07    68.8  1455.2    78.6 1447.38
    98.3 1428.12   108.1 1416.91   127.7 1389.61   147.4 1367.22   157.2 1366.02
   176.9 1345.76   186.7 1338.26   196.5 1333.96   206.3 1331.92     216 1331.61
     226 1333.88   245.6 1344.48   265.3 1349.54   284.9 1360.44   324.2 1386.39
   363.5 1421.51   373.4 1423.07   402.8 1449.59   412.7 1454.08   432.3  1455.6
   442.2 1459.19   461.8 1480.09   471.6 1483.64   481.4 1490.28   491.3  1499.7
#Mann= 3 , 0 , 0
       0      .1       0   206.3    .045       0     216      .1       0
Bank Sta=206.3,216
XS Rating Curve= 0 ,0
Exp/Cntr=0.3,0.1

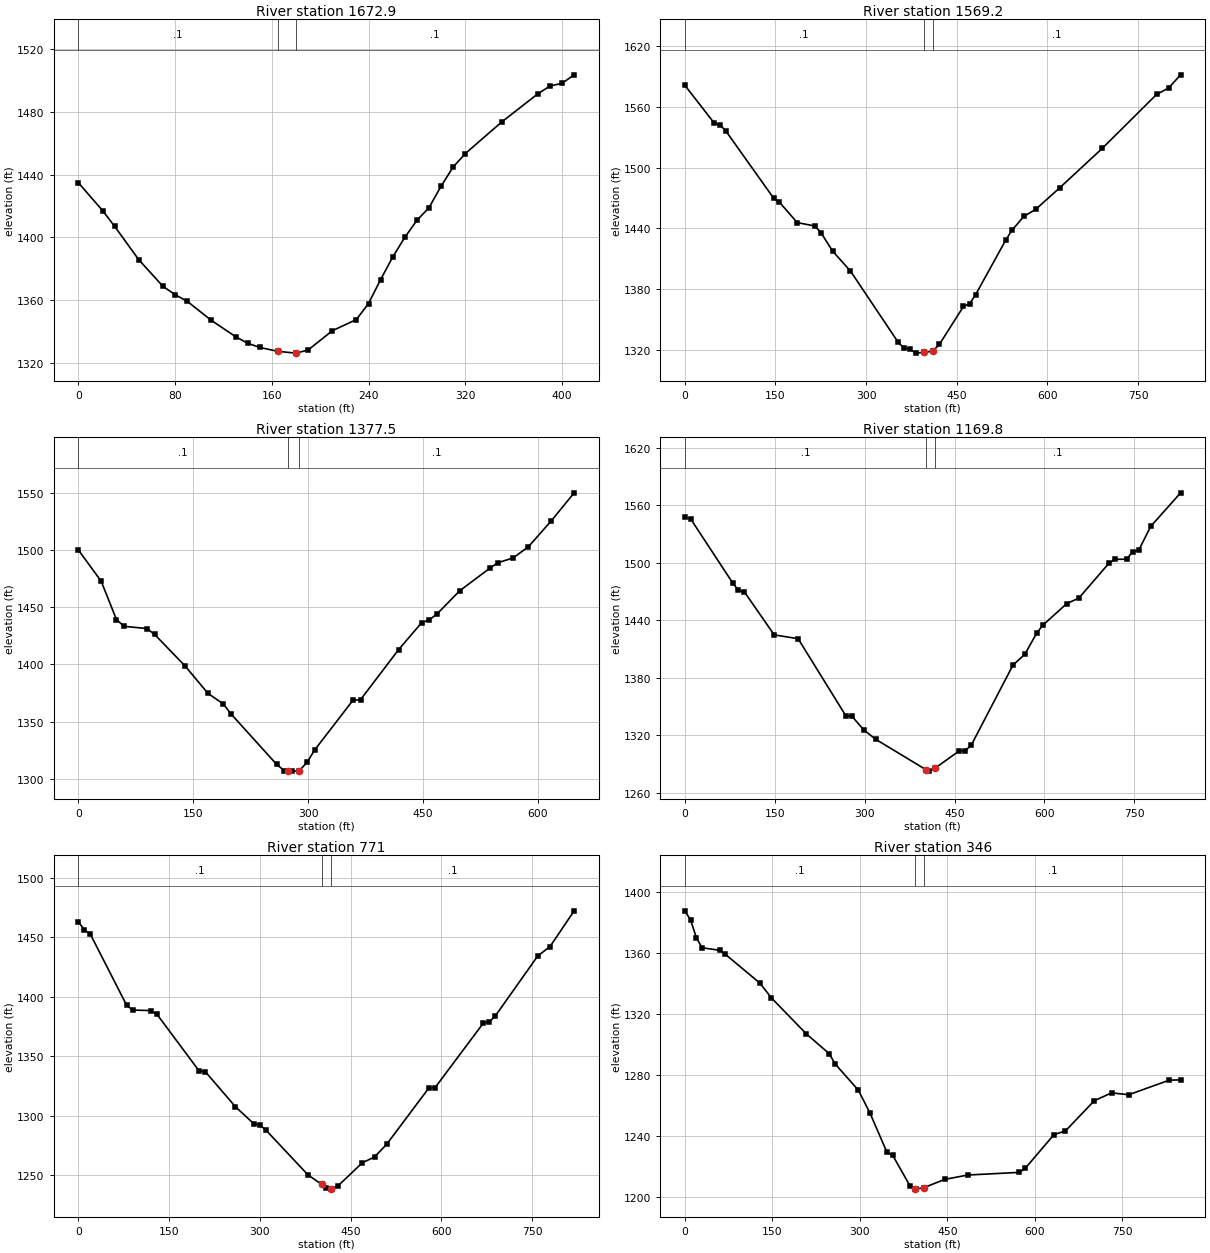
Type RM Length L Ch R = 1 ,1672.9  ,103.2,103.6,102.8
XS GIS Cut Line= 2
     1939471.773      306900.797     1939289.877      306533.274
#Sta/Elev= 30
       0 1434.84      20 1417.11      30 1407.04      50 1385.73      70 1368.77
      80 1363.47      90 1359.26     110 1347.07     130 1336.74     140 1332.51
     150 1329.84   164.8 1327.36   179.8  1326.2     190 1328.15     210 1340.44
     230 1347.63     240 1357.81     250 1373.05     260 1387.41     270 1399.95
     280 1410.82     290 1418.87     300 1432.58     310 1444.79   320.1 1453.42
   350.1 1473.49   380.1 1491.52   390.1 1496.45   400.1 1498.21   410.1 1503.59
#Mann= 3 , 0 , 0
       0      .1       0   164.8    .045       0   179.8      .1       0
Bank Sta=164.8,179.8
XS Rating Curve= 0 ,0
Exp/Cntr=0.3,0.1

Type RM Length L Ch R = 1 ,1569.2  ,186.8,191.6,197.6
XS GIS Cut Line= 3
     1939661.626      307068.705     1939485.966      306696.915
     1939281.251      306342.604
#Sta/Elev= 30
       0 1581.48      49 1543.89    58.7 1542.14    68.5 1535.84   146.9 1469.99
   156.6    1466     186 1445.81   215.4 1442.44   225.2 1435.93   244.8 1417.49
   274.1 1397.96   352.5 1328.06   362.2 1321.99     372 1321.06   381.8 1316.86
     395 1317.52     410 1318.79   421.2 1325.44   461.1 1362.99   471.1 1365.61
   481.1 1374.54     531 1428.47     541 1438.02   560.9 1451.88   580.9 1459.03
   620.8 1480.42   690.6 1519.07   780.5 1572.37   800.4 1578.75   820.4  1591.8
#Mann= 3 , 0 , 0
       0      .1       0     395    .045       0     410      .1       0
Bank Sta=395,410
XS Rating Curve= 0 ,0
Exp/Cntr=0.3,0.1

Type RM Length L Ch R = 1 ,1377.5  ,201.3,207.6,214
XS GIS Cut Line= 2
     1939731.558      306912.768     1939586.041      306282.195
#Sta/Elev= 30
       0 1499.95    29.9 1472.52    49.8 1439.13    59.7 1433.29    89.6 1431.34
    99.6 1426.19   139.4 1398.65   169.2 1374.78   189.2 1365.62   199.1 1357.01
   258.9 1312.81   268.8  1307.4   273.1 1307.22   278.8 1306.97   288.1 1307.05
   298.7 1314.79   308.6 1325.53   358.4 1368.73   368.4 1369.34   418.2 1413.06
     448 1436.38     458 1438.92   467.9 1443.86   497.8 1464.26   537.6 1484.21
   547.6 1488.76   567.5 1492.91   587.4 1502.64   617.3 1525.25   647.2 1549.72
#Mann= 3 , 0 , 0
       0      .1       0   273.1    .045       0   288.1      .1       0
Bank Sta=273.1,288.1
XS Rating Curve= 0 ,0
Exp/Cntr=0.3,0.1

Type RM Length L Ch R = 1 ,1169.8  ,395.5,398.8,403
XS GIS Cut Line= 3
       1939851.5       307021.44     1939875.675      306514.618
     1939962.436       306206.89
#Sta/Elev= 30
       0 1547.44      10 1545.34    79.6 1479.08    89.5 1470.96    99.5 1469.39
   149.2 1424.61     189 1420.68   268.6 1340.29   278.6 1339.98   298.5 1325.58
   318.4 1315.76   402.8 1283.88   407.9 1282.56   417.8 1285.76   457.6 1303.61
   467.6 1303.92   477.6 1309.34   547.4 1393.08   567.4 1404.56   587.3  1426.8
   597.3 1434.76   637.3 1457.33   657.3 1462.96   707.2 1499.11   717.2  1503.4
   737.2 1503.56   747.2 1511.58   757.2  1512.9   777.2 1537.77   827.1 1572.77
#Mann= 3 , 0 , 0
       0      .1       0   402.8    .045       0   417.8      .1       0
Bank Sta=402.8,417.8
XS Rating Curve= 0 ,0
Exp/Cntr=0.3,0.1

Type RM Length L Ch R = 1 ,771     ,422.4,424.9,426.5
XS GIS Cut Line= 3
     1940170.103      307129.675     1940249.076      306727.923
     1940342.946      306328.978
#Sta/Elev= 30
       0  1463.1      10 1456.47      20  1452.6    79.9 1392.88    89.9 1388.94
   119.8  1388.5   129.8 1385.45   199.7 1337.63   209.7 1337.17   259.6 1307.61
   289.6 1293.47   299.6 1292.23   309.6 1288.16   379.5 1250.27   401.9 1242.38
   409.4 1238.97   416.9 1238.47   419.4  1238.3   429.4 1241.21   469.4  1260.5
   489.4 1265.34   509.4 1275.95   579.4 1323.52   589.4  1323.6   669.3 1378.02
   679.3    1379   689.3 1384.18   759.3 1434.54   779.3 1442.24   819.3  1472.4
#Mann= 3 , 0 , 0
       0      .1       0   401.9    .045       0   416.9      .1       0
Bank Sta=401.9,416.9
XS Rating Curve= 0 ,0
Exp/Cntr=0.3,0.1

Type RM Length L Ch R = 1 ,346     ,341.4,345.9,350.4
XS GIS Cut Line= 3
     1940394.778      307208.583     1940597.663      306991.279
     1940757.031      306462.154
#Sta/Elev= 30
       0 1387.44     9.9 1381.51    19.8 1369.83    29.7 1363.25    59.5  1361.6
    69.4    1359   128.8 1340.06   148.6 1330.34   208.1 1306.94   247.7 1293.81
   257.6 1287.17   297.3 1270.05     317 1255.32   346.6 1229.22   356.5  1227.2
   386.1 1207.21     395 1205.35     396 1205.14     410 1206.13   445.3 1211.49
   484.8 1214.37   573.6 1216.12   583.5 1218.75   632.8 1240.85   652.5 1243.26
   701.9 1263.04   731.5  1268.2   761.1 1266.97   830.2 1276.51   849.9 1276.71
#Mann= 3 , 0 , 0
       0      .1       0     395    .045       0     410      .1       0
Bank Sta=395,410
XS Rating Curve= 0 ,0
Exp/Cntr=0.3,0.1

Chan Stop Cuts=-1
Use User Specified Reach Order=0
Composite Channel Slope=5